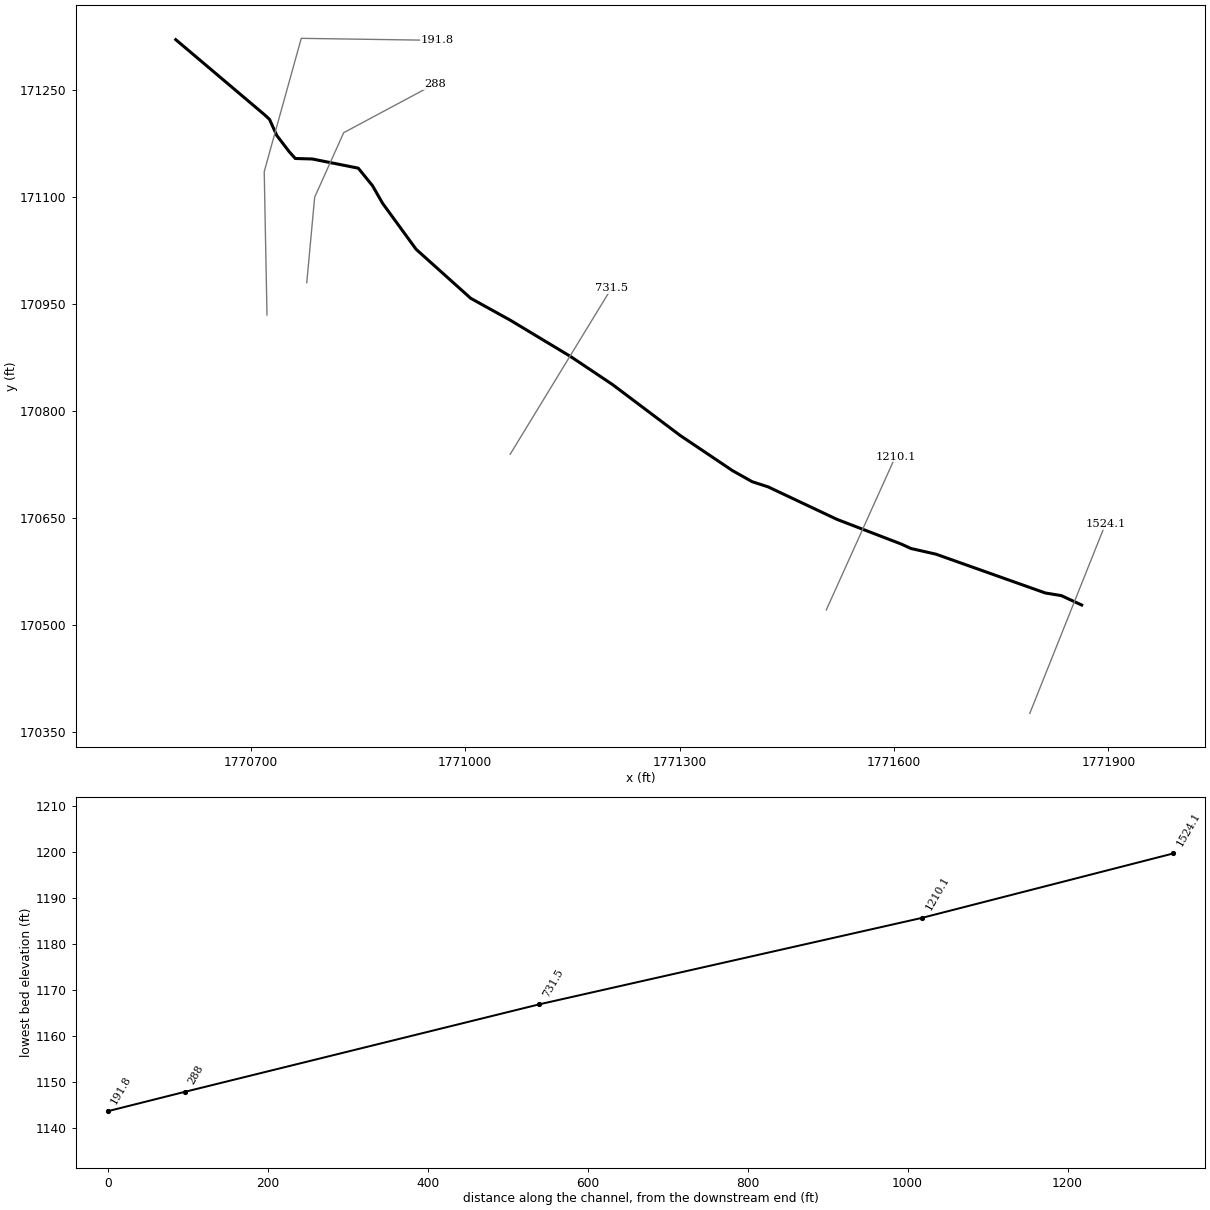
--- Huntingshirt Branch.prj (project) ---

Proj Title=Huntingshirt Branch
Current Plan=p01
Default Exp/Contr=0,0
English Units
Geom File=g01
Flow File=f01
Plan File=p01
BEGIN DESCRIPTION:
END DESCRIPTION:
DSS Export Rating Curves= 0
DSS Export Rating Curve Sorted= 0
DSS Export Volume Flow Curves= 0
DXF OffsetX= 0
DXF OffsetY= 0
DXF ScaleX= 0
DXF ScaleY= 0

--- Huntingshirt Branch.p01 (plan) ---

Plan Title=Floodplain
Program Version=4.00
Geom File=g01
Flow File=f01
K Sum by GR=0
Std Step Tol=0.01
Critical Tol=0.01
Num of Std Step Trials=20
Max Error Tol=0.3
Flow Tol Ratio=0.001
Split Flow NTrial=30
Split Flow Tol=0.02
Split Flow Ratio=0.02
Log Output Level=0
Friction Slope Method=1
Unsteady Friction Slope Method=2
Unsteady Bridges Friction Slope Method=1
Global Log Level=0
CheckData=False
Run HTab=0
Run UNet=0
Run PostProcess=0
UNET Theta=0
UNET Theta Warmup=0
UNET ZTol=0
UNET ZSATol=0
UNET MxIter=0
UNET MaxInSteps=0
UNET DtIC=0
UNET DtMin=0
UNET MaxCRTS=0
UNET WFStab=0
UNET SFStab=0
UNET WFX=0
UNET SFX=0
UNET DSS MLevel=0
UNET DZMax Abort=0
UNET Convert EG Bridges=0
UNET Use Existing IB Tables=0
UNET Froude Limit=0
UNET Froude Power=0
Write IC File=0
Echo Input=False
Echo Output=False
Write Detailed=0

--- Huntingshirt Branch.f01 (steady flow) ---

Flow Title=NFF Regression Equation
Program Version=4.00
Number of Profiles=1
Profile Names=P100yr
River Rch & RM=Huntingshirt ...,Main      ,1524.1
505.6819
River Rch & RM=Huntingshirt ...,Main      ,1524.1
626.1458
River Rch & RM=Huntingshirt ...,Main      ,1524.1
505.6819
River Rch & RM=Huntingshirt ...,Main      ,1210.1
607.6362
Boundary for River Rch & Prof#=Huntingshirt ...,Main      ,1
Up Type=0
Dn Type=3
Dn Slope=0.040484

--- Huntingshirt Branch.g01 (geometry) ---

Geom Title=Geometry
Program Version=4.00

River Reach=Huntingshirt ...,Main
Reach XY= 28
     1771862.615      170527.534     1771834.165      170540.728
      1771811.63      170544.475     1771794.117      170550.704
     1771658.658      170598.883     1771623.821      170606.781
     1771610.012       170613.11     1771520.344      170647.597
     1771423.779      170693.252     1771401.389      170700.556
     1771374.182      170715.887     1771300.702      170765.353
     1771205.833      170836.894     1771181.031      170853.509
     1771147.019      170876.293     1771063.454      170926.721
     1771007.602      170957.704     1770931.157      171026.464
     1770884.256      171090.952     1770870.186      171115.574
     1770850.254      171140.197     1770785.766      171153.095
     1770762.078      171153.759     1770753.443      171163.473
     1770736.172      171186.141     1770726.065      171208.629
     1770719.265      171214.955     1770594.874      171320.405

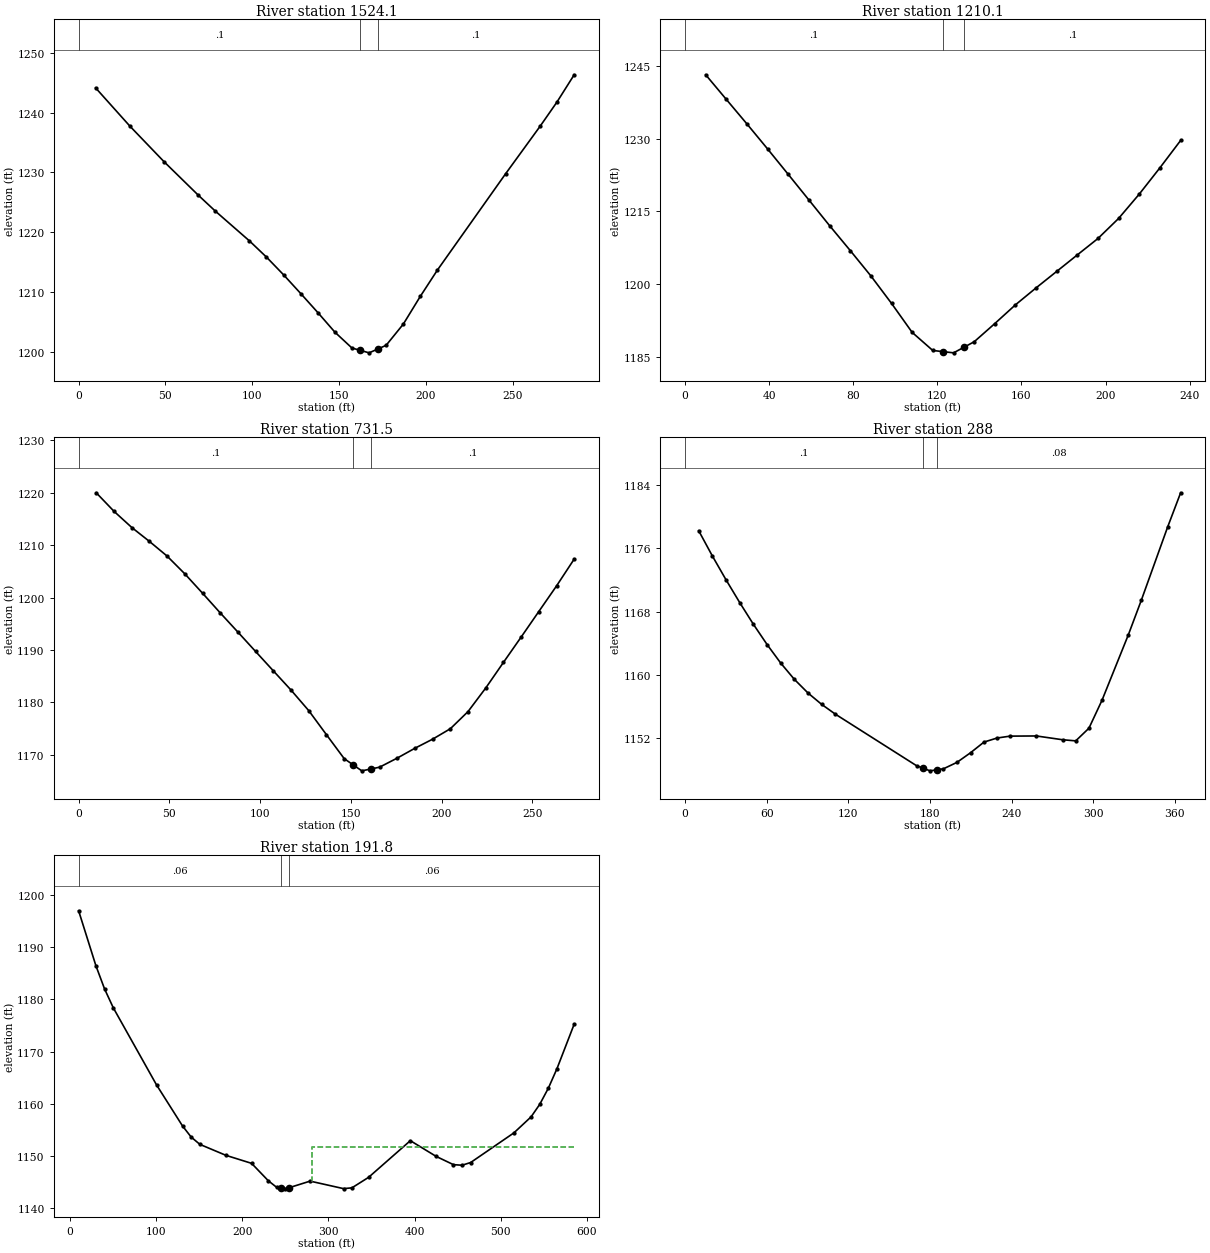
Type RM Length L Ch R = 1 ,1524.1  ,314.8,314,313.1
XS GIS Cut Line= 2
     1771789.967      170375.609     1771895.639      170640.684
#Sta/Elev= 23
     9.8 1244.12    29.5 1237.73    49.2 1231.77    68.9 1226.17    78.7 1223.51
    98.4 1218.51   108.2  1215.8   118.1 1212.82   127.9 1209.71   137.8 1206.51
   147.6 1203.24   157.4 1200.59   162.3 1200.19   167.3 1199.78   172.3 1200.42
   177.1 1201.04     187 1204.59   196.8 1209.24   206.6 1213.62     246 1229.79
   265.7 1237.67   275.5 1241.76   285.4 1246.32
#Mann= 3 , 0 , 0
       0      .1       0   162.3    .045       0   172.3      .1       0
Bank Sta=162.3,172.3
XS Rating Curve= 0 ,0
Exp/Cntr=0.3,0.1

Type RM Length L Ch R = 1 ,1210.1  ,481.1,478.6,476.1
XS GIS Cut Line= 2
      1771505.19      170520.684     1771601.906       170735.61
#Sta/Elev= 26
     9.8 1243.27    19.6 1238.18    29.5 1233.06    39.3  1227.9    49.1 1222.65
    58.9 1217.37    68.7 1212.08    78.6 1206.89    88.4 1201.65    98.2 1195.98
     108 1189.99   117.8 1186.25   122.7 1186.01   127.7 1185.76   132.7 1186.93
   137.5 1188.05   147.3 1191.81   157.1 1195.68   166.9 1199.18   176.8 1202.62
   186.6 1206.03   196.4 1209.42   206.2 1213.56     216 1218.58   225.9 1224.06
   235.7 1229.69
#Mann= 3 , 0 , 0
       0      .1       0   122.7    .045       0   132.7      .1       0
Bank Sta=122.7,132.7
XS Rating Curve= 0 ,0
Exp/Cntr=0.3,0.1

Type RM Length L Ch R = 1 ,731.5   ,440.6,443.5,446.5
XS GIS Cut Line= 3
     1771062.815      170738.968     1771133.784      170855.568
     1771204.753      170972.169
#Sta/Elev= 30
     9.7    1220    19.5 1216.46    29.3 1213.37      39 1210.72    48.7 1207.93
    58.5 1204.53    68.3 1200.82      78 1197.08    87.8 1193.39    97.5 1189.71
   107.2 1186.04     117 1182.35   126.8 1178.41   136.5 1173.84   146.3 1169.26
     151 1168.13     156 1166.93     161 1167.28   165.8 1167.63   175.5 1169.36
   185.3 1171.25     195 1172.97   204.8 1174.97   214.5 1178.23   224.3 1182.75
     234 1187.61   243.8 1192.47   253.5 1197.33   263.3 1202.23     273 1207.34
#Mann= 3 , 0 , 0
       0      .1       0     151    .045       0     161      .1       0
Bank Sta=151,161
XS Rating Curve= 0 ,0
Exp/Cntr=0.3,0.1

Type RM Length L Ch R = 1 ,288     ,90.8,96.2,104.6
XS GIS Cut Line= 4
     1770778.142      170979.464     1770789.219      171099.466
     1770829.835      171189.929     1770957.222      171258.238
#Sta/Elev= 30
      10 1178.22    20.1 1175.01    30.1 1172.01    40.2 1169.12    50.2 1166.39
    60.3 1163.82    70.3 1161.48    80.3 1159.43    90.4 1157.69   100.4 1156.26
   110.5 1155.02   170.1 1148.51     175 1148.19     180 1147.86     185 1147.99
   189.9 1148.12   199.8 1148.93   209.8 1150.15   219.7  1151.5   229.3 1152.01
   238.9 1152.25   258.2 1152.27   277.5 1151.79   287.1 1151.65   296.8 1153.25
   306.4 1156.78   325.7 1165.03   335.3 1169.43   354.6 1178.67   364.2 1183.02
#Mann= 3 , 0 , 0
       0      .1       0     175    .045       0     185     .08       0
Bank Sta=175,185
XS Rating Curve= 0 ,0
Exp/Cntr=0.3,0.1

Type RM Length L Ch R = 1 ,191.8   ,203.6,191.8,176.9
XS GIS Cut Line= 4
       1770722.5      170934.317     1770718.643      171135.346
     1770770.469      171322.271     1770960.464      171319.435
#Sta/Elev= 30
    10.1    1197    30.2 1186.43    40.2    1182    50.3 1178.39   100.5 1163.59
   130.7  1155.7   140.7 1153.58   150.8 1152.18     181 1150.08   210.8 1148.54
   230.2  1145.2   239.9 1143.94   244.6  1143.8   249.6 1143.65   254.6 1143.88
   278.7 1145.13   317.5 1143.69   327.2 1143.84   346.5 1145.85     395 1152.89
     425 1149.87     445 1148.29     455 1148.18     465  1148.7   515.1 1154.38
   535.1 1157.46   545.1 1159.85   555.1 1162.95   565.1 1166.69   585.1 1175.24
#Mann= 3 , 0 , 0
    10.1     .06       0   244.6    .045       0   254.6     .06       0
#XS Ineff= 2 , 0
                          280.87         1151.73
Permanent Ineff=
       F       F
Bank Sta=244.6,254.6
XS Rating Curve= 0 ,0
Exp/Cntr=0.3,0.1

Chan Stop Cuts=-1
Use User Specified Reach Order=0